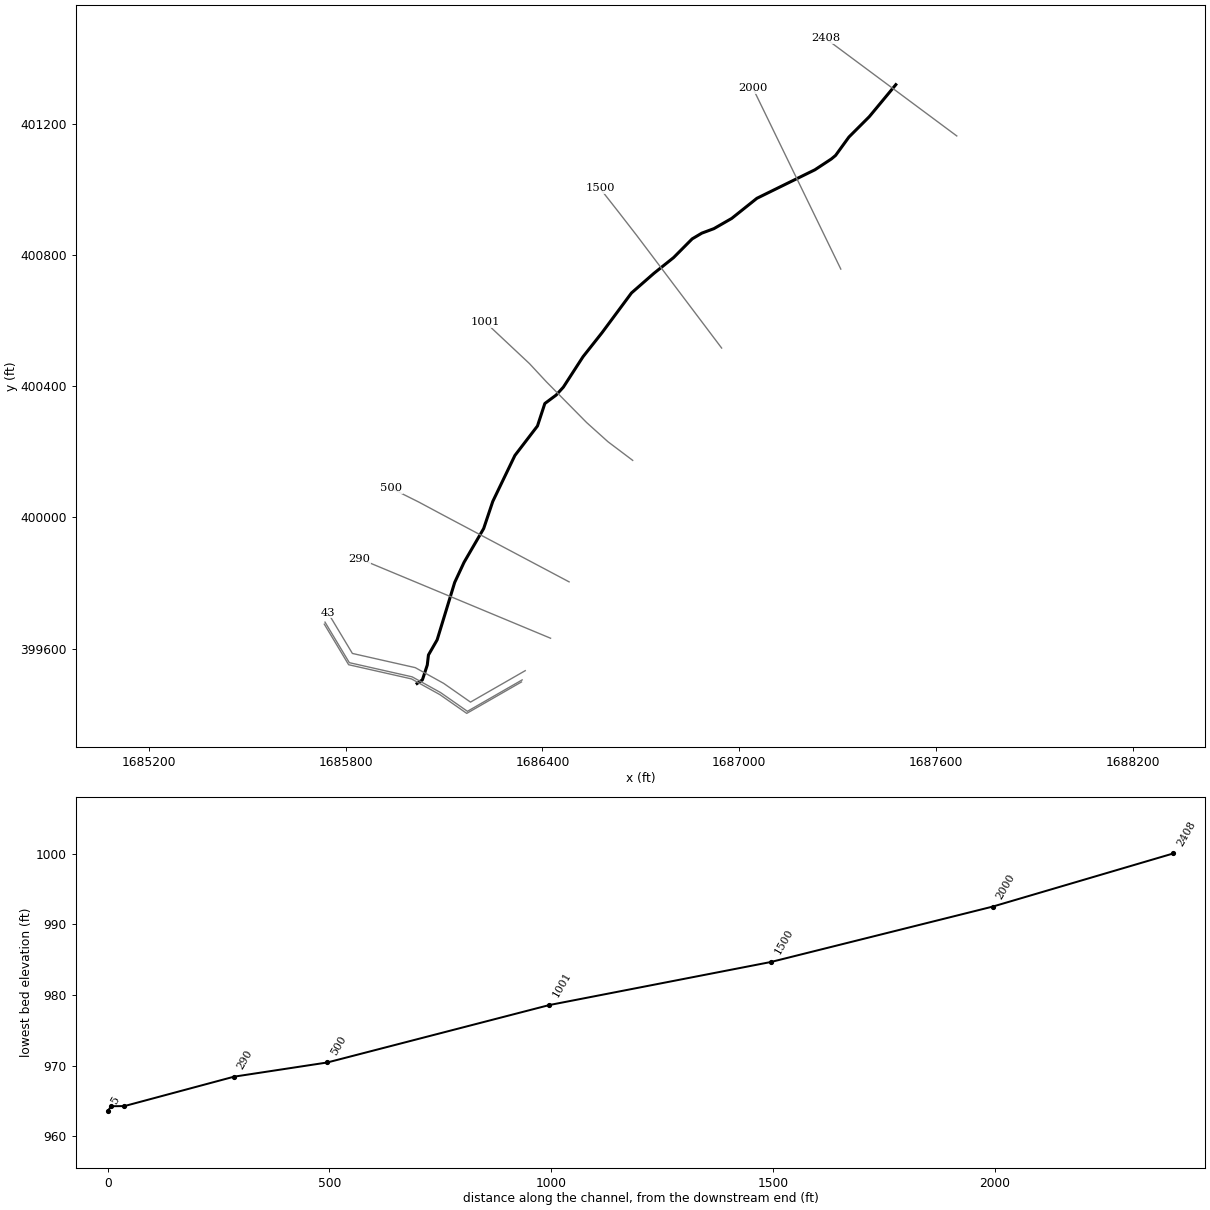
--- MORGANRN2.prj (project) ---

Proj Title=MORGANRN2
Current Plan=p01
Default Exp/Contr=0,0
English Units
Geom File=g01
Flow File=f01
Plan File=p01
BEGIN DESCRIPTION:
---------- MODELED AS PART OF WVEMD CTP PROGRAM, 2023----------
Stream Name: Morgan Run (II)
Flood Zone:  AFH
Wetzel County, WV
HEC-RAS Version: RAS 6.3
Vertical Datum: NAVD88
Projection: NAD 1983 StatePlane West Virginia S FIPS 4702 (US Feet)
Terrain: 1-meter West Virginia FEMA R3 South Central (collected 2018-2020)
Land Use: 2019 NLCD
Hydrologic Method:
WV 2010 Regional Regression Equations
Additional Model Notes:
None
END DESCRIPTION:
DSS Export Rating Curves= 0
DSS Export Rating Curve Sorted= 0
DSS Export Volume Flow Curves= 0
DXF OffsetX= 0
DXF OffsetY= 0
DXF ScaleX= 0
DXF ScaleY= 0

--- MORGANRN2.p01 (plan) ---

Plan Title=Floodplain
Program Version=4.00
Geom File=g01
Flow File=f01
K Sum by GR=0
Std Step Tol=0.01
Critical Tol=0.01
Num of Std Step Trials=20
Max Error Tol=0.3
Flow Tol Ratio=0.001
Split Flow NTrial=30
Split Flow Tol=0.02
Split Flow Ratio=0.02
Log Output Level=0
Friction Slope Method=1
Unsteady Friction Slope Method=2
Unsteady Bridges Friction Slope Method=1
Global Log Level=0
CheckData=False
Run HTab=0
Run UNet=0
Run PostProcess=0
UNET Theta=0
UNET Theta Warmup=0
UNET ZTol=0
UNET ZSATol=0
UNET MxIter=0
UNET MaxInSteps=0
UNET DtIC=0
UNET DtMin=0
UNET MaxCRTS=0
UNET WFStab=0
UNET SFStab=0
UNET WFX=0
UNET SFX=0
UNET DSS MLevel=0
UNET DZMax Abort=0
UNET Convert EG Bridges=0
UNET Use Existing IB Tables=0
UNET Froude Limit=0
UNET Froude Power=0
Write IC File=0
Echo Input=False
Echo Output=False
Write Detailed=0

--- MORGANRN2.f01 (steady flow) ---

Flow Title=Flow
Program Version=6.31
Number of Profiles= 1
Profile Names=F01pct
River Rch & RM=MORGANRN2,Main            ,2408
     636
Boundary for River Rch & Prof#=MORGANRN2,Main            , 1
Up Type= 0
Dn Type= 3
Dn Slope=0.01714
DSS Import GetInterval= 0
DSS Import GetPeak= 0
DSS Import FillOption= 0

--- MORGANRN2.g01 (geometry) ---

Geom Title=Geometry
Program Version=6.31

River Reach=MORGANRN2       ,Main
Reach XY= 30
     1687477.733      401319.808     1687396.782      401222.153
     1687334.677      401160.048     1687293.987      401103.939
     1687281.138      401093.232     1687231.026      401060.251
     1687054.133      400973.304     1686977.465      400912.056
      1686923.07      400880.789     1686886.235      400867.083
     1686856.681      400849.522     1686800.144      400792.557
     1686740.181      400744.586     1686671.651      400684.622
     1686582.134      400563.838     1686523.883      400490.169
     1686463.954      400397.448     1686442.024      400373.326
     1686407.485      400347.558     1686385.008      400279.028
     1686316.204      400189.117      1686248.77      400049.042
     1686220.972      399966.273     1686161.187      399863.359
     1686132.633      399802.086     1686079.094      399626.895
     1686052.622      399580.792     1686049.052      399550.156
      1686034.18      399504.945     1686017.976      399493.871

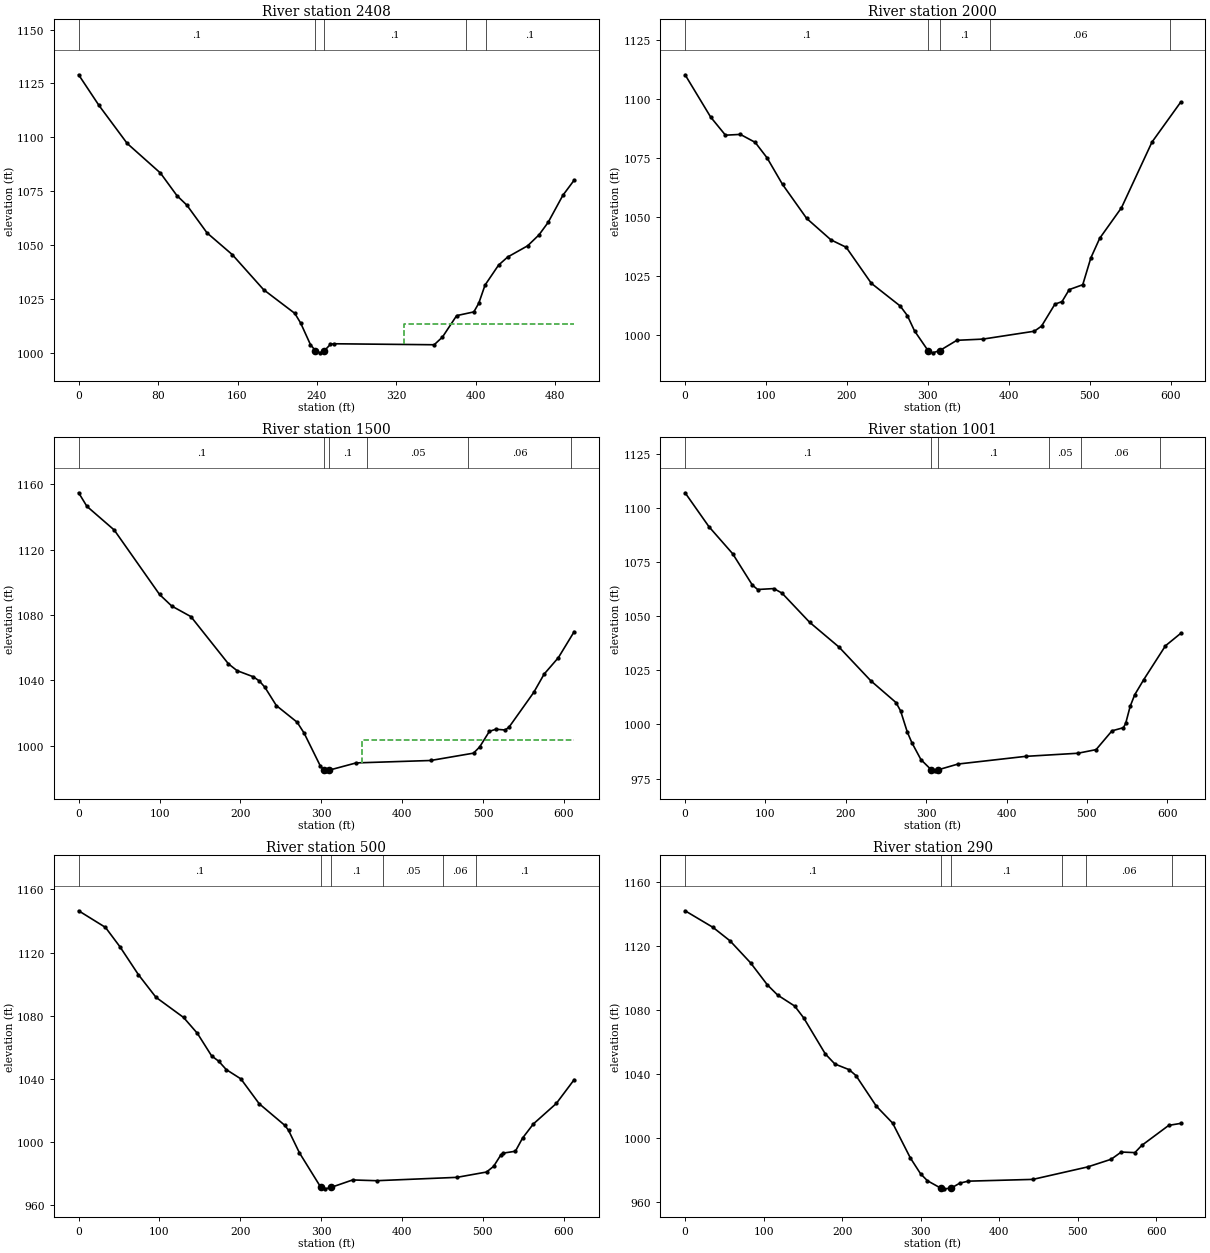
Type RM Length L Ch R = 1 ,2408    ,410,407.6,403.9
XS GIS Cut Line= 2
1687663.57567644401163.3917846851687262.99142877401461.048135387
#Sta/Elev= 30
       0 1129.03    20.4 1114.88    48.9 1097.19    82.4 1083.45      99 1072.99
     109 1068.57   129.3 1055.71   154.8  1045.6   186.3 1029.36   217.7 1018.38
   223.6 1013.89   233.5 1003.85   238.5 1001.08   243.4 1000.07  247.55 1001.08
   253.5 1003.98   256.8 1004.28   358.1 1003.82   366.4 1007.38   380.7 1017.33
     398 1019.05     403 1023.08   409.3  1031.5   422.9 1040.75   432.1 1044.51
   452.2 1049.71   463.6 1054.76   472.8 1060.54   487.7 1073.14499.0662 1080.16
#Mann= 5 ,-1,0
       0      .1       0   238.5    .045       0  247.55      .1       0
     390     .06       0     410      .1       0
#XS Ineff= 2 , 0
                          327.64         1013.38
Permanent Ineff=
       F       F
Bank Sta=238.5,247.55
XS Rating Curve= 0 ,0
Exp/Cntr(USF)=0,0
Exp/Cntr=0.3,0.1

Type RM Length L Ch R = 1 ,2000    ,498.9,500,501.1
XS GIS Cut Line= 6
1687309.94677018400757.4576414231687268.96883376400841.777682751
 1687197.9407606400987.9325741681687154.23087426401077.873995334
1687121.44845951401145.3298971651687042.22388043     401308.3486
#Sta/Elev= 30
       0 1110.15    31.6 1092.26    49.9  1084.6    68.3 1084.93    86.6 1081.57
   101.3 1075.02   120.4 1063.79   150.3 1049.38   180.3 1040.31   199.1 1037.19
   230.2 1021.94   265.8 1012.36   274.7  1008.3   283.6  1001.8  300.29  993.47
     306  992.53   314.7  993.47   335.9  997.83   368.1  998.34   431.7 1001.68
   440.6 1003.84   457.1 1013.12   465.9 1014.21   474.8 1019.28   491.5 1021.34
   501.5 1032.68   512.5    1041   539.4 1053.92   577.1 1081.69612.5001 1098.54
#Mann= 5 ,-1,0
       0      .1       0  300.29    .045       0   314.7      .1       0
  376.25     .06       0  598.75      .1       0
Bank Sta=300.29,314.7
XS Rating Curve= 0 ,0
Exp/Cntr(USF)=0,0
Exp/Cntr=0.3,0.1

Type RM Length L Ch R = 1 ,1500    ,498.7,499.4,499.1
XS GIS Cut Line= 6
1686946.60268059400516.6815481781686837.47232142 400661.39549759
1686792.31591567400721.2779237631686686.95031276400861.002709925
1686633.32902892400930.1577553451686575.41838358401003.905967429
#Sta/Elev= 30
       0 1154.76    10.2 1146.48      44 1131.98     100 1092.57     115 1085.51
   138.8 1079.01   185.2  1050.1   195.9 1045.95   215.9 1042.22   223.4 1039.63
   230.2 1035.81   244.4  1024.6   270.1 1014.42   278.7 1007.77   298.7  987.72
  303.36   985.1   305.4  984.68   309.7   985.1     343  989.53   435.2  991.01
   488.1   995.5   495.7  999.29   507.7 1008.81   515.6 1010.13   527.2 1009.67
     532  1011.4   562.5 1032.62   575.4 1043.86     593 1053.92612.5259  1069.8
#Mann= 6 ,-1,0
       0      .1       0  303.36    .045       0   309.7      .1       0
  356.25     .05       0  481.25     .06       0  608.76      .1       0
#XS Ineff= 2 , 0
                          350.77         1003.82
Permanent Ineff=
       F       F
Bank Sta=303.36,309.7
XS Rating Curve= 0 ,0
Exp/Cntr(USF)=0,0
Exp/Cntr=0.3,0.1

Type RM Length L Ch R = 1 ,1001    ,500.1,500.6,502.5
XS GIS Cut Line= 6
  1686675.400139400174.1871544271686600.09385918400230.923589513
1686534.94832018400289.4730130881686412.00007525 400414.01213409
1686360.42767183400469.4529680911686226.16776976400595.277519584
#Sta/Elev= 30
       0 1106.91    29.7 1091.25    59.2 1078.78    83.7 1064.31    90.3 1062.27
   110.4  1062.7   120.6  1060.6   154.9 1047.16   191.5 1035.71   231.1 1020.14
   262.4 1010.11   268.1 1006.29   276.5  996.49   282.1  991.63   293.5  983.74
  306.35  979.04   310.5  978.58  314.71  979.04   339.6  981.72   423.7  985.26
   488.8   986.7   511.4  988.37   531.2  997.04   545.4   998.5   548.2 1000.43
   553.8 1008.33   559.5  1013.7   570.8 1020.73   597.7 1036.28616.6198    1042
#Mann= 6 ,-1,0
       0      .1       0  306.35    .045       0  314.71      .1       0
   452.6     .05       0   492.6     .06       0  591.53      .1       0
Bank Sta=306.35,314.71
XS Rating Curve= 0 ,0
Exp/Cntr(USF)=0,0
Exp/Cntr=0.3,0.1

Type RM Length L Ch R = 1 ,500     ,209.6,210.1,210.7
XS GIS Cut Line= 6
1686481.44842717399803.7679477481686398.61361909399847.670419008
1686166.67609084399970.5983227491686100.40850684400005.720955923
1686023.26266375400047.0115557611685939.02398708400089.098085761
#Sta/Elev= 30
       0 1146.42    33.2  1135.9    51.3 1123.51    73.9 1106.02    95.6 1091.69
   129.8  1078.9   146.9 1068.84   164.5 1054.57   173.2 1051.24   182.6 1045.92
   200.7 1040.02   223.3 1024.32     255 1010.63   259.6  1007.5   273.1  993.24
  299.61  971.35   304.8  970.44   312.2  971.35   338.9  976.07   368.5  975.59
   467.9  977.71   504.5  981.08   513.2  984.62   522.3  991.95   525.2  993.05
   540.2  994.23   549.1 1002.58   562.5 1011.54   590.8 1024.46612.9177 1039.53
#Mann= 6 ,-1,0
       0      .1       0  299.61    .045       0   312.2      .1       0
  376.25     .05       0  451.25     .06       0  491.25      .1       0
Bank Sta=299.61,312.2
XS Rating Curve= 0 ,0
Exp/Cntr(USF)=0,0
Exp/Cntr=0.3,0.1

Type RM Length L Ch R = 1 ,290     ,247.6,247.3,245.7
XS GIS Cut Line= 2
 1686424.9698729399631.8535772831685842.32997562399874.491412487
#Sta/Elev= 30
       0 1142.18    35.6 1131.79    57.3 1123.36    83.3  1109.7   104.9 1095.82
   117.9  1089.5   139.6 1082.64   151.1 1075.22   178.6 1052.72   190.8 1046.42
   208.9  1042.9   217.6 1039.22   243.6 1020.06   264.3 1009.52   286.9  987.73
   299.9  977.84   308.6  973.51   325.6  968.88   330.2  968.43   338.9  968.88
   349.9     972   360.6  973.23   442.9  974.33   512.7  982.12   542.6   986.9
   555.5  991.42   572.9  991.07   581.5  995.52     616 1008.09631.1437 1009.32
#Mann= 6 ,-1,0
       0      .1       0   325.6    .045       0   338.9      .1       0
     480     .05       0     510     .06       0     620      .1       0
Bank Sta=325.6,338.9
XS Rating Curve= 0 ,0
Exp/Cntr(USF)=0,0
Exp/Cntr=0.3,0.1

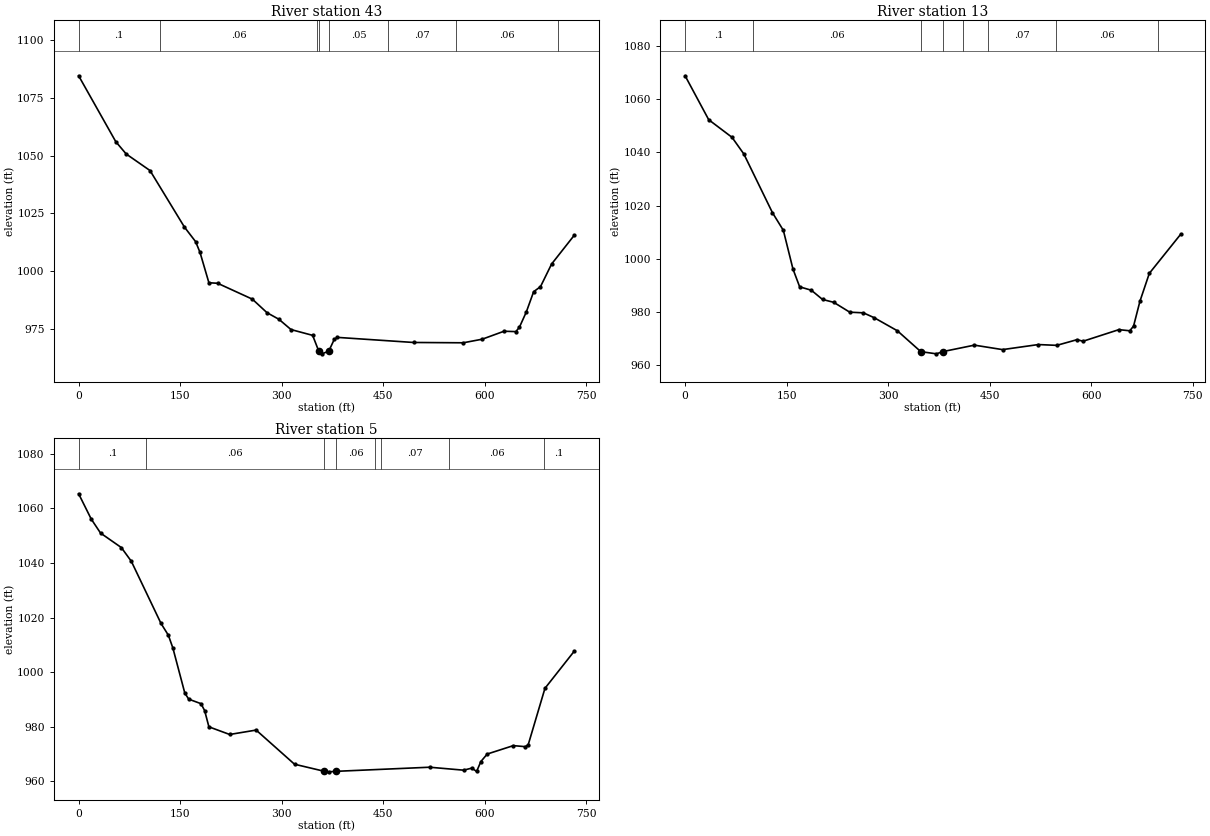
Type RM Length L Ch R = 1 ,43      ,32,30,30
XS GIS Cut Line= 6
1686347.69667697  399532.94388651686180.78657377399437.125123553
1686098.87698609399494.3072885371686012.33100666399542.216670011
1685820.69348077399585.4896597291685746.51121268399709.126773208
#Sta/Elev= 30
       0  1084.6    54.9 1056.08    70.3 1050.75   105.5 1043.58   156.3 1019.14
   172.9  1012.8   179.4 1008.13   192.5  995.03   205.4   994.8   256.7  987.93
   278.3  982.08     296  979.21   313.8  974.77   345.8  972.26  354.85  965.43
   359.5  964.26   369.6  965.42   377.8  970.55   382.4  971.38   494.9  969.18
   568.3  969.04   596.3  970.59   628.6  974.04   646.1  973.88   651.4   975.8
   661.6  982.41   672.4  991.16   682.5  993.32   698.9 1003.12732.2768 1015.53
#Mann= 8 ,-1,0
       0      .1       0     120     .06       0  352.35     .05       0
  354.85    .045       0   369.6     .05       0  457.45     .07       0
  557.45     .06       0  708.09      .1       0
Bank Sta=354.85,369.6
XS Rating Curve= 0 ,0
Exp/Cntr(USF)=0,0
Exp/Cntr=0.3,0.1

Type RM Length L Ch R = 1 ,13      ,15.2,7.8,6.6
XS GIS Cut Line= 6
1686338.35898398399504.8365342141686171.44888078399409.017771267
 1686089.5392931399466.1999362521686002.99331366399514.109317725
1685811.35578777399557.3823074431685737.17351968399681.019420923
#Sta/Elev= 30
       0 1068.82    34.9 1052.29    69.3 1045.68    86.8 1039.41   129.1 1017.32
   145.2 1010.68   159.4  996.14   169.3  989.44   186.5  988.17   203.1  984.69
   219.6  983.62   243.3  979.91   263.5  979.66   279.5  977.82   313.7  972.91
  348.33  965.06   371.5  964.24   380.5  965.06   427.5  967.51   469.1  965.83
     522  967.73   549.2  967.43   579.2  969.57   588.1  968.98     641  973.34
   657.1  972.91   662.7  974.66   672.1  983.99     686  994.51732.2768 1009.19
#Mann= 8 ,-1,0
       0      .1       0     100     .06       0  348.33    .045       0
   380.5     .06       0  411.27     .05       0  447.45     .07       0
  547.45     .06       0  698.09      .1       0
Bank Sta=348.33,380.5
XS Rating Curve= 0 ,0
Exp/Cntr(USF)=0,0
Exp/Cntr=0.3,0.1

Type RM Length L Ch R = 1 ,5       ,,,
XS GIS Cut Line= 6
1686336.25093431 399498.556592141686169.34083111399402.737829193
1686087.43124343399459.919994177  1686000.885264399507.829375651
1685809.24773811399551.1023653681685735.06547002399674.739478848
#Sta/Elev= 30
       0 1065.34    18.6 1056.09    32.4 1050.95    63.1 1045.65    77.8 1040.65
   121.7 1017.88   132.6 1013.55   139.3 1008.84   156.9  992.37   162.7  990.14
   180.8  988.49   186.2  985.96   192.5  980.01   223.2  977.21   262.3  978.82
     319  966.32  362.84  963.74   369.3  963.53   380.6  963.72   518.7  965.22
   568.9  964.14   581.1   964.9   588.1  963.66   594.4   967.3   603.8  970.05
   642.4  973.13   660.3  972.74   664.4  973.49   689.1  994.11732.2768 1007.67
#Mann= 8 ,-1,0
       0      .1       0     100     .06       0  362.84    .045       0
   380.6     .06       0  437.45     .05       0  447.45     .07       0
  547.45     .06       0  688.09      .1       0
Bank Sta=362.84,380.6
XS Rating Curve= 0 ,0
Exp/Cntr(USF)=0,0
Exp/Cntr=0.3,0.1
LCMann Table=0

Chan Stop Cuts=-1
Use User Specified Reach Order=0
Composite Channel Slope=5